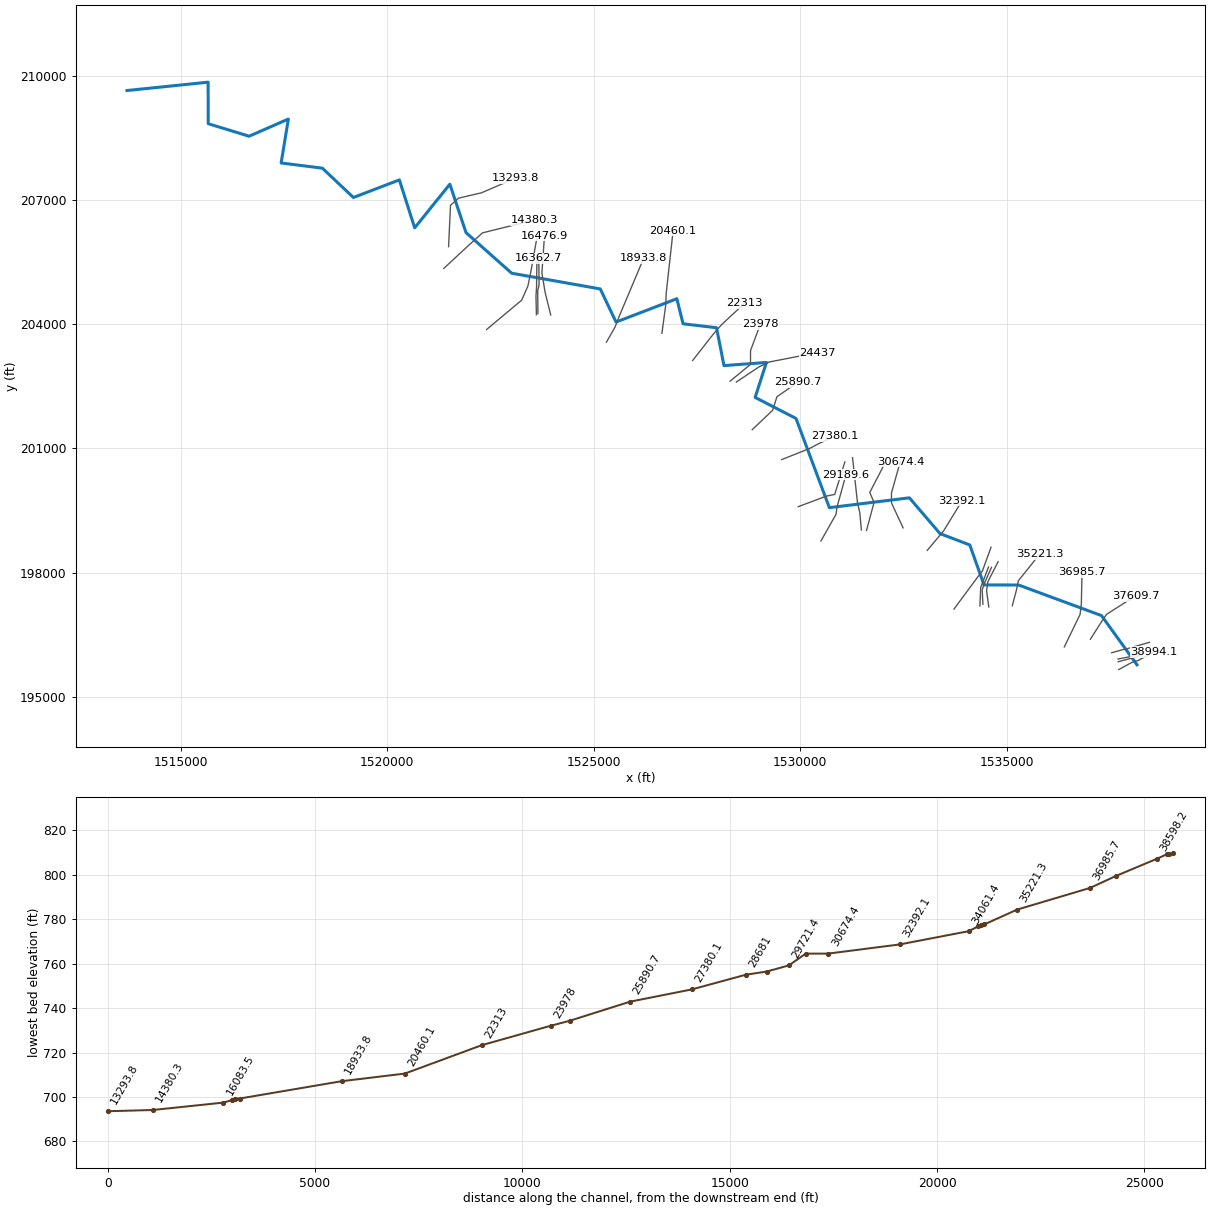
--- LTHRBRKCR.prj (project) ---

Proj Title=LTHRBRKCR
Current Plan=p01
Default Exp/Contr=0,0
English Units
Geom File=g01
Flow File=f01
Plan File=p01
BEGIN DESCRIPTION:
END DESCRIPTION:
DSS Export Rating Curves= 0
DSS Export Rating Curve Sorted= 0
DSS Export Volume Flow Curves= 0
DXF OffsetX= 0
DXF OffsetY= 0
DXF ScaleX= 0
DXF ScaleY= 0

--- LTHRBRKCR.p01 (plan) ---

Plan Title=Floodplain
Program Version=4.00
Geom File=g01
Flow File=f01
K Sum by GR=0
Std Step Tol=0.01
Critical Tol=0.01
Num of Std Step Trials=20
Max Error Tol=0.3
Flow Tol Ratio=0.001
Split Flow NTrial=30
Split Flow Tol=0.02
Split Flow Ratio=0.02
Log Output Level=0
Friction Slope Method=1
Unsteady Friction Slope Method=2
Unsteady Bridges Friction Slope Method=1
Global Log Level=0
CheckData=False
Run HTab=0
Run UNet=0
Run PostProcess=0
UNET Theta=0
UNET Theta Warmup=0
UNET ZTol=0
UNET ZSATol=0
UNET MxIter=0
UNET MaxInSteps=0
UNET DtIC=0
UNET DtMin=0
UNET MaxCRTS=0
UNET WFStab=0
UNET SFStab=0
UNET WFX=0
UNET SFX=0
UNET DSS MLevel=0
UNET DZMax Abort=0
UNET Convert EG Bridges=0
UNET Use Existing IB Tables=0
UNET Froude Limit=0
UNET Froude Power=0
Write IC File=0
Echo Input=False
Echo Output=False
Write Detailed=0

--- LTHRBRKCR.f01 (steady flow) ---

Flow Title=NFF Regression Equation
Program Version=4.10
Number of Profiles= 1
Profile Names=P100yr
River Rch & RM=LTHRBRKCR,Main            ,38994.1
1081.343
River Rch & RM=LTHRBRKCR,Main            ,37609.7
1100.003
River Rch & RM=LTHRBRKCR,Main            ,36985.7
1183.277
River Rch & RM=LTHRBRKCR,Main            ,34433.5
1254.542
River Rch & RM=LTHRBRKCR,Main            ,34061.4
1562.526
River Rch & RM=LTHRBRKCR,Main            ,30674.4
1627.959
River Rch & RM=LTHRBRKCR,Main            ,29189.6
1699.324
River Rch & RM=LTHRBRKCR,Main            ,28681
 1881.76
River Rch & RM=LTHRBRKCR,Main            ,24437
1952.176
River Rch & RM=LTHRBRKCR,Main            ,23978
2004.176
River Rch & RM=LTHRBRKCR,Main            ,20460.1
 2091.92
River Rch & RM=LTHRBRKCR,Main            ,16476.9
2218.374
River Rch & RM=LTHRBRKCR,Main            ,16083.5
3219.504
River Rch & RM=LTHRBRKCR,Main            ,4276.9
3453.647
River Rch & RM=LTHRBRKCR,Main            ,3896
3874.104
River Rch & RM=LTHRBRKCR,Main            ,430.4
3908.819
Boundary for River Rch & Prof#=LTHRBRKCR,Main            , 1
Up Type= 0
Dn Type= 3
Dn Slope=0.00056
DSS Import GetInterval= 0
DSS Import GetPeak= 0
DSS Import FillOption= 0

--- LTHRBRKCR.g01 (geometry) ---

Geom Title=USGS 10m DEM
Program Version=4.10

River Reach=LTHRBRKCR       ,Main
Reach XY= 30
     1538155.883      195769.116     1537296.153      196959.333
     1535288.558      197698.742      1534451.14      197700.821
     1534106.899      198667.072     1533385.042      198941.972
     1532644.069      199806.555      1530706.23      199568.864
     1529897.726      201725.607      1528908.15      202233.981
     1529181.569      203079.137     1528153.803      203003.265
     1527973.256      203918.452     1527162.943      204014.348
      1527012.86      204620.041     1525539.953      204056.281
     1525158.409      204856.226     1523013.765      205236.603
     1521907.658      206216.374     1521515.364      207388.925
     1520663.543      206333.666      1520292.72       207492.82
     1519179.836      207067.188     1518428.169      207776.272
     1517429.939      207901.628     1517604.191      208963.771
     1516653.916      208548.386     1515664.016      208851.249
     1515661.224      209855.062     1513697.301      209653.177

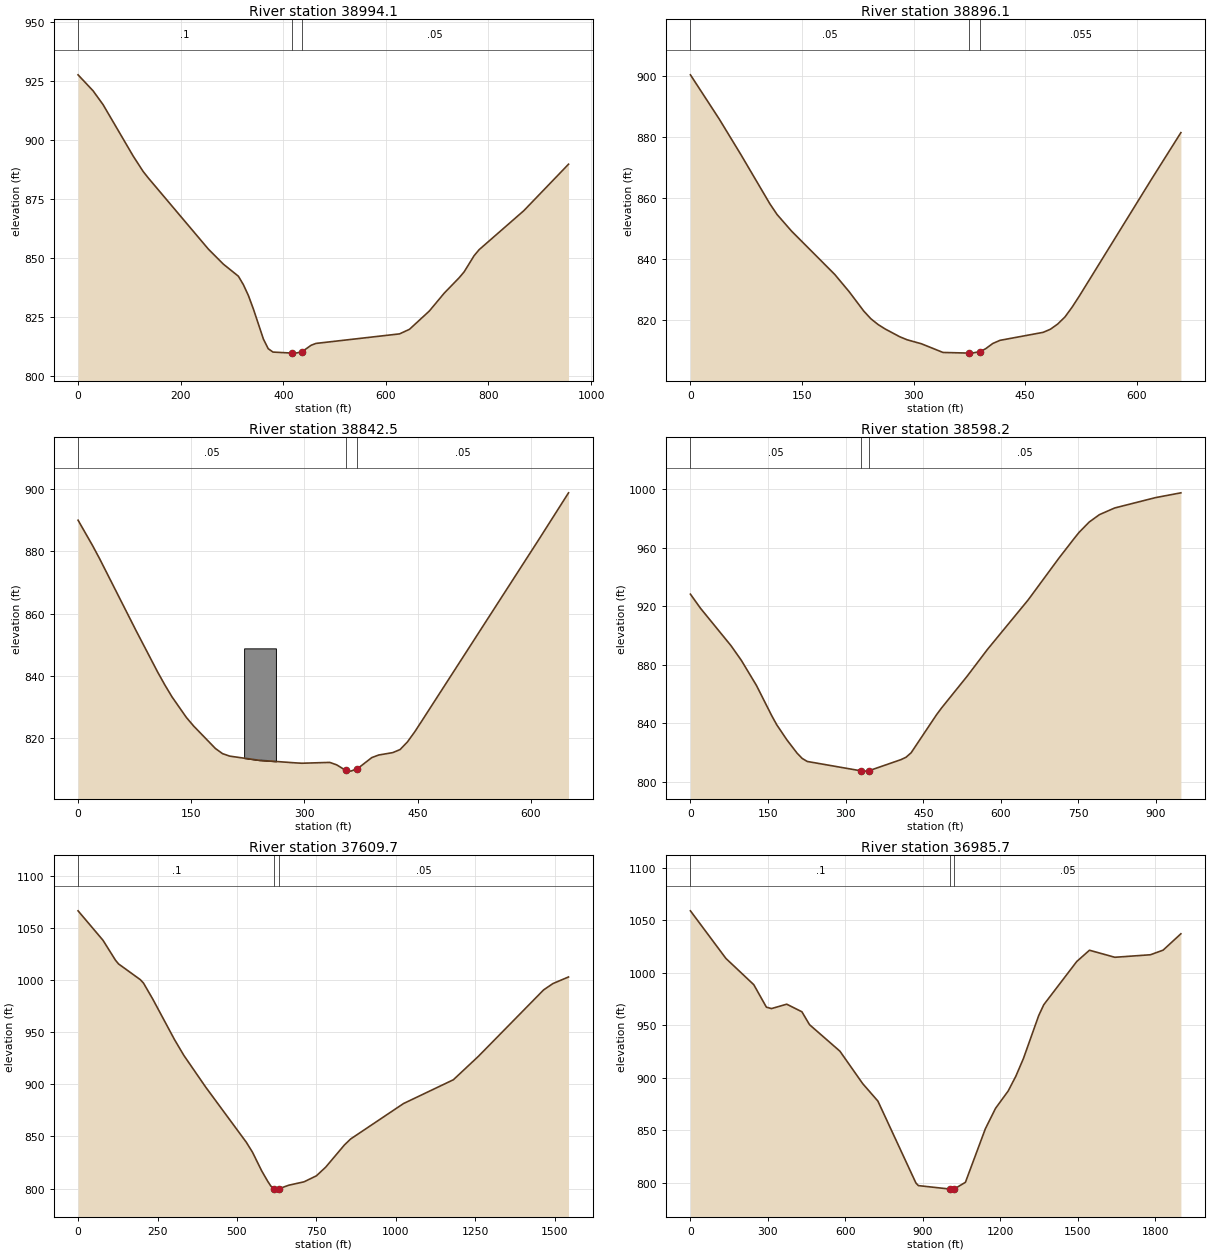
Type RM Length L Ch R = 1 ,38994.1 ,98.9,98,97.5
XS GIS Cut Line= 4
     1537716.225      195655.438     1538033.065      195829.049
     1538176.294      195870.282     1538569.089      196080.785
#Sta/Elev= 30
       0  927.61    29.3  920.82    48.8  914.95   107.4  893.18   126.9  886.61
   136.7  883.92   253.9  853.72   283.2  847.32   312.5   842.2   322.2  838.64
     332  834.02   341.8  828.26   361.3  815.52   370.6  811.47   379.9  810.03
   417.2  809.59   423.9  809.58   435.8  810.07   454.4  812.93   463.8   813.7
   626.6  817.74     646  819.68   684.7  827.44   713.8  835.04   742.8  841.54
   752.5  844.04   771.9  850.88   781.6  853.42   868.8  869.98     956   889.7
#Mann= 3 , 0 , 0
       0      .1       0   417.2    .045       0   435.8     .05       0
Bank Sta=417.2,435.8
XS Rating Curve= 0 ,0
Exp/Cntr=0.3,0.1

Type RM Length L Ch R = 1 ,38896.1 ,51,53.6,56
XS GIS Cut Line= 4
     1537703.204       195844.24     1538022.214      195928.876
     1538124.211      195954.917     1538326.034      196052.573
#Sta/Elev= 30
       0   900.3    38.8   885.8      68  874.13   106.8  858.09   116.5  854.58
   135.9  849.17   194.2  834.93   213.6  829.27     233     823   242.7  820.44
   252.4  818.56   262.1  817.08   281.5  814.57   291.2  813.59   310.6  812.27
   339.6  809.43   374.6  809.22   377.9  809.21   389.6  809.69     397  810.66
   406.6  812.37   416.2  813.39   474.3  816.01   484.1  817.04   493.8  818.72
   503.6  821.04   513.3  824.28     523  827.92   620.5  866.33   659.5  881.38
#Mann= 3 , 0 , 0
       0     .05       0   374.6    .045       0   389.6    .055       0
Bank Sta=374.6,389.6
XS Rating Curve= 0 ,0
Exp/Cntr=0.3,0.1

Type RM Length L Ch R = 1 ,38842.5 ,247.5,244.3,241
XS GIS Cut Line= 4
     1537696.693      195909.344     1537978.811      195963.598
     1538100.339      196009.171     1538317.353      196093.806
#Sta/Elev= 30
       0  890.03    19.2  881.88    28.7  877.57    76.6  854.62   105.3  841.24
   114.9  837.06   124.5  833.17   143.6  826.53   153.2  823.78     182  816.56
   191.5  814.89   201.1  814.09   239.4  812.78   287.3  811.94   296.6  811.81
   333.6  812.08   342.9  811.27   352.2  809.88     355  809.69   361.4  809.27
     370     810   389.3  813.63   398.5  814.46   417.1  815.23   426.8  816.22
   436.5  818.67   446.2  821.92   455.9  825.54   611.2  884.02     650  898.84
#Mann= 3 , 0 , 0
       0     .05       0     355    .045       0     370     .05       0
#Block Obstruct= 1 ,-1
  220.07  262.21  848.78
Bank Sta=355,370
XS Rating Curve= 0 ,0
Exp/Cntr=0.3,0.1

Type RM Length L Ch R = 1 ,38598.2 ,970.6,988.4,1004.1
XS GIS Cut Line= 4
     1537542.614      196061.254     1537807.371      196135.039
     1537926.728       196161.08     1538456.242       196312.99
#Sta/Elev= 30
       0  928.26    19.6  918.55    78.5  892.98    98.2  883.09   127.6  865.82
     157   845.2   166.9  838.86   186.5  828.56   206.1   819.5     216  815.87
   225.8   813.8  329.24807.4084   340.6  807.19  344.94807.4515   406.8  815.04
   416.7  816.69   426.5  819.73   475.7  845.81   485.5  850.47   534.7  872.08
   574.1  890.48   652.8  924.36   711.8  952.73   741.3  966.21   751.1  970.53
   770.8  977.63   790.5  982.67     820  987.23   898.7   994.3   947.9  997.59
#Mann= 3 , 0 , 0
       0     .05       0  329.24    .045       0  344.94     .05       0
Bank Sta=329.24,344.94
XS Rating Curve= 0 ,0
Exp/Cntr=0.3,0.1

Type RM Length L Ch R = 1 ,37609.7 ,612.5,624,634.7
XS GIS Cut Line= 4
      1537027.48      196388.135     1537327.046      196859.576
     1537420.796       196991.52     1538115.241      197432.492
#Sta/Elev= 30
       0 1066.28    78.4 1038.07   117.6    1019   127.4 1015.37     196 1000.25
   205.8  997.02   235.2  981.57   303.8  942.61   333.2   927.5   401.8  897.16
   529.2  844.44   548.8  834.82   577.6  817.01   596.6  807.01   606.2  802.46
   617.8  799.77   625.2  799.45   632.8  799.96   663.3  803.23   710.9  806.46
   749.8  812.21   779.2  820.55   837.9  841.77   857.5  847.52    1024  881.52
  1180.7  904.31    1259  926.64  1464.7  990.49  1494.1  996.56    1543 1002.86
#Mann= 3 , 0 , 0
       0      .1       0   617.8    .045       0   632.8     .05       0
Bank Sta=617.8,632.8
XS Rating Curve= 0 ,0
Exp/Cntr=0.3,0.1

Type RM Length L Ch R = 1 ,36985.7 ,1764.2,1764.5,1762.6
XS GIS Cut Line= 4
     1536395.478      196201.893     1536777.423      196987.484
     1536807.805       197234.88     1536825.166      198011.789
#Sta/Elev= 30
       0 1058.91   137.4 1013.62   245.4  988.62   294.4   967.2   314.1  965.89
     373  970.06   431.8  962.85   461.3  950.58   579.1  925.34   667.4  894.44
   726.3  877.82   873.5  799.88   883.1  797.41  1007.4  794.08  1007.7  794.07
  1022.4  794.28  1065.2  800.55  1142.4  851.46  1181.8  870.93    1231   887.5
  1260.5  901.52    1290  918.41    1349  959.16  1368.7  969.54  1496.6 1010.72
  1545.8 1021.41  1644.1  1014.7  1781.8  1017.1    1831 1021.49  1899.9 1037.06
#Mann= 3 , 0 , 0
       0      .1       0  1007.4    .045       0  1022.4     .05       0
Bank Sta=1007.4,1022.4
XS Rating Curve= 0 ,0
Exp/Cntr=0.3,0.1

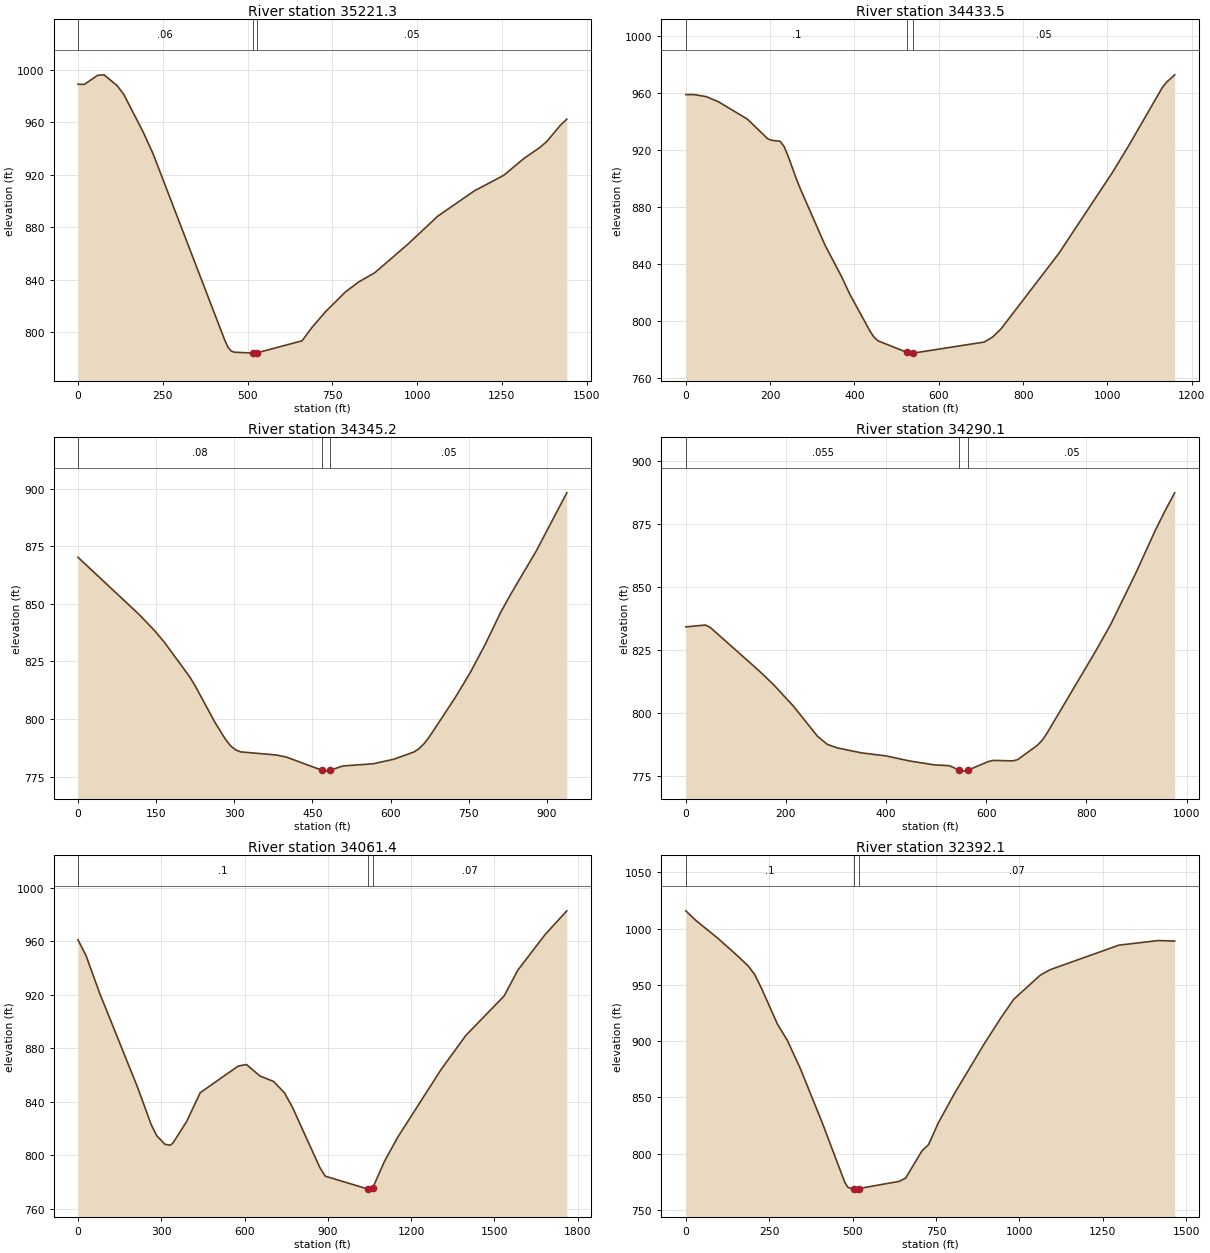
Type RM Length L Ch R = 1 ,35221.3 ,785.3,787.8,788.4
XS GIS Cut Line= 4
     1535136.074      197196.381     1535236.769      197578.326
     1535281.908      197800.548     1535795.796      198439.437
#Sta/Elev= 30
       0  988.97    19.3  988.96    57.8  995.81    77.1  996.18   115.6  987.91
   134.9  981.36   192.7  952.39   221.6  935.99   432.8  794.21   442.2  788.85
   451.7   785.9   461.1  784.99   514.7  784.36   517.8  784.28   527.3  784.47
   660.8  793.64   690.1  803.84   729.1  815.55   787.7  830.61   826.7  838.27
   875.5  845.54   973.2  867.28    1061  888.55  1168.4  907.73  1256.2  919.75
  1314.8  932.43  1363.6  941.12  1383.1  945.57  1422.2  957.62  1441.7  962.42
#Mann= 3 , 0 , 0
       0     .06       0   514.7    .045       0   527.3     .05       0
Bank Sta=514.7,527.3
XS Rating Curve= 0 ,0
Exp/Cntr=0.3,0.1

Type RM Length L Ch R = 1 ,34433.5 ,92.5,88.3,84.4
XS GIS Cut Line= 4
      1534566.63      197168.604     1534513.592      197553.933
     1534541.803      197773.117     1534792.324      198262.354
#Sta/Elev= 30
       0  959.18    19.4  959.18    48.6  957.74    77.8  954.08   145.9  941.96
   194.5   928.1   204.2  927.04   223.6  926.44   233.4  922.55   243.1  915.61
   262.6  899.61   272.3  892.58   330.6  853.17   369.5  831.29     389  818.98
     437  793.01   446.6  788.76   456.2  786.23   524.9  778.11   533.1  777.63
   539.9  777.67   708.1  785.42   727.7  788.94   747.4  794.56   884.8  847.64
  1012.4  904.72  1051.6  923.84  1130.2  964.08    1140  967.79  1159.6  973.06
#Mann= 3 , 0 , 0
       0      .1       0   524.9    .045       0   539.9     .05       0
Bank Sta=524.9,539.9
XS Rating Curve= 0 ,0
Exp/Cntr=0.3,0.1

Type RM Length L Ch R = 1 ,34345.2 ,53.7,55.1,59.2
XS GIS Cut Line= 4
     1534424.269      197234.576     1534406.908       197585.27
     1534465.935      197751.937     1534632.602      198126.937
#Sta/Elev= 30
       0  870.24     117  845.48   146.3  838.57   165.8  833.35   214.6  818.27
   224.3  814.67   263.3   798.4   282.8   791.3   292.6  788.42   302.4  786.64
   312.1  785.74   380.6  784.39   400.2  783.47   468.6  777.73   478.8  777.38
   483.6  777.71   508.3  779.61     567  780.59   606.1  782.54   645.2  785.72
     655  787.19   664.7   789.4   674.5   792.3   723.4  809.07   752.7  820.07
     782  832.56   811.3  846.31   830.8  854.26   879.7  873.01   938.3  898.23
#Mann= 3 , 0 , 0
       0     .08       0   468.6    .045       0   483.6     .05       0
Bank Sta=468.6,483.6
XS Rating Curve= 0 ,0
Exp/Cntr=0.3,0.1

Type RM Length L Ch R = 1 ,34290.1 ,234.4,228.7,219.1
XS GIS Cut Line= 4
     1534351.352      197192.909     1534370.796      197640.739
     1534434.685       197804.02     1534559.685      198133.881
#Sta/Elev= 30
       0  834.16      39  834.88    48.7  833.94   146.2  816.72   175.4  811.16
   214.4  802.75   263.1  790.65   282.6  787.48   302.1  786.08   350.8  784.09
   399.5   782.9   448.2  780.82     497  779.31   526.2     779   545.7  777.28
   555.4  776.84   564.1  777.28   604.1  780.65   613.8   781.1     653  780.91
   662.8  781.42     702  787.09   711.8  789.09   721.6     792   819.6  824.89
     849  835.32     898  855.25   937.1  872.28   956.7  880.14   976.3  887.41
#Mann= 3 , 0 , 0
       0    .055       0   545.7    .045       0   564.1     .05       0
Bank Sta=545.7,564.1
XS Rating Curve= 0 ,0
Exp/Cntr=0.3,0.1

Type RM Length L Ch R = 1 ,34061.4 ,1673.8,1669.3,1664.9
XS GIS Cut Line= 4
     1533723.603      197116.824     1534294.755      197887.354
      1534412.81      198040.131      1534621.23      198612.093
#Sta/Elev= 30
       0  961.15    29.4  949.09    78.3  921.06   215.3  850.45   264.2  822.63
   283.8  814.58   313.2  808.16   332.8  807.48   342.6  809.23   391.5  825.22
   440.4  846.76   577.4  866.68   606.8  867.82   655.7  859.22   704.7  855.15
   743.8  846.66   773.2   835.6     871  790.89   890.6  784.32 1043.46774.7238
    1046  774.61  1061.7  775.46  1103.9  795.32  1152.2  813.54  1309.3  864.48
  1397.7  889.67  1535.1  919.09  1584.2   938.3  1682.4  964.94    1761  982.78
#Mann= 3 , 0 , 0
       0      .1       0 1043.46    .045       0  1061.7     .07       0
Bank Sta=1043.46,1061.7
XS Rating Curve= 0 ,0
Exp/Cntr=0.3,0.1

Type RM Length L Ch R = 1 ,32392.1 ,1699,1717.7,1730.6
XS GIS Cut Line= 4
     1533076.902      198536.963     1533298.314      198799.593
     1533470.189      199002.718     1533918.105      199731.885
#Sta/Elev= 30
       0 1015.74    29.4 1007.38    98.2  990.81     157  975.22   186.5  966.92
   206.1  959.38   225.7  947.65   274.8  915.03   304.2  900.77   343.5  875.53
     410  826.74   476.6  774.58     486  770.16   502.7  768.67   505.1  768.63
   517.7  769.12   639.1  775.49   658.8  778.36     708  802.68   727.6  808.13
   757.1  827.58   806.3  854.07   894.8  897.79     944  920.51   983.4  937.35
  1062.1  958.51  1091.6  963.42  1298.1  985.26  1416.2  989.34  1465.4   988.9
#Mann= 3 , 0 , 0
       0      .1       0   502.7    .045       0   517.7     .07       0
Bank Sta=502.7,517.7
XS Rating Curve= 0 ,0
Exp/Cntr=0.3,0.1

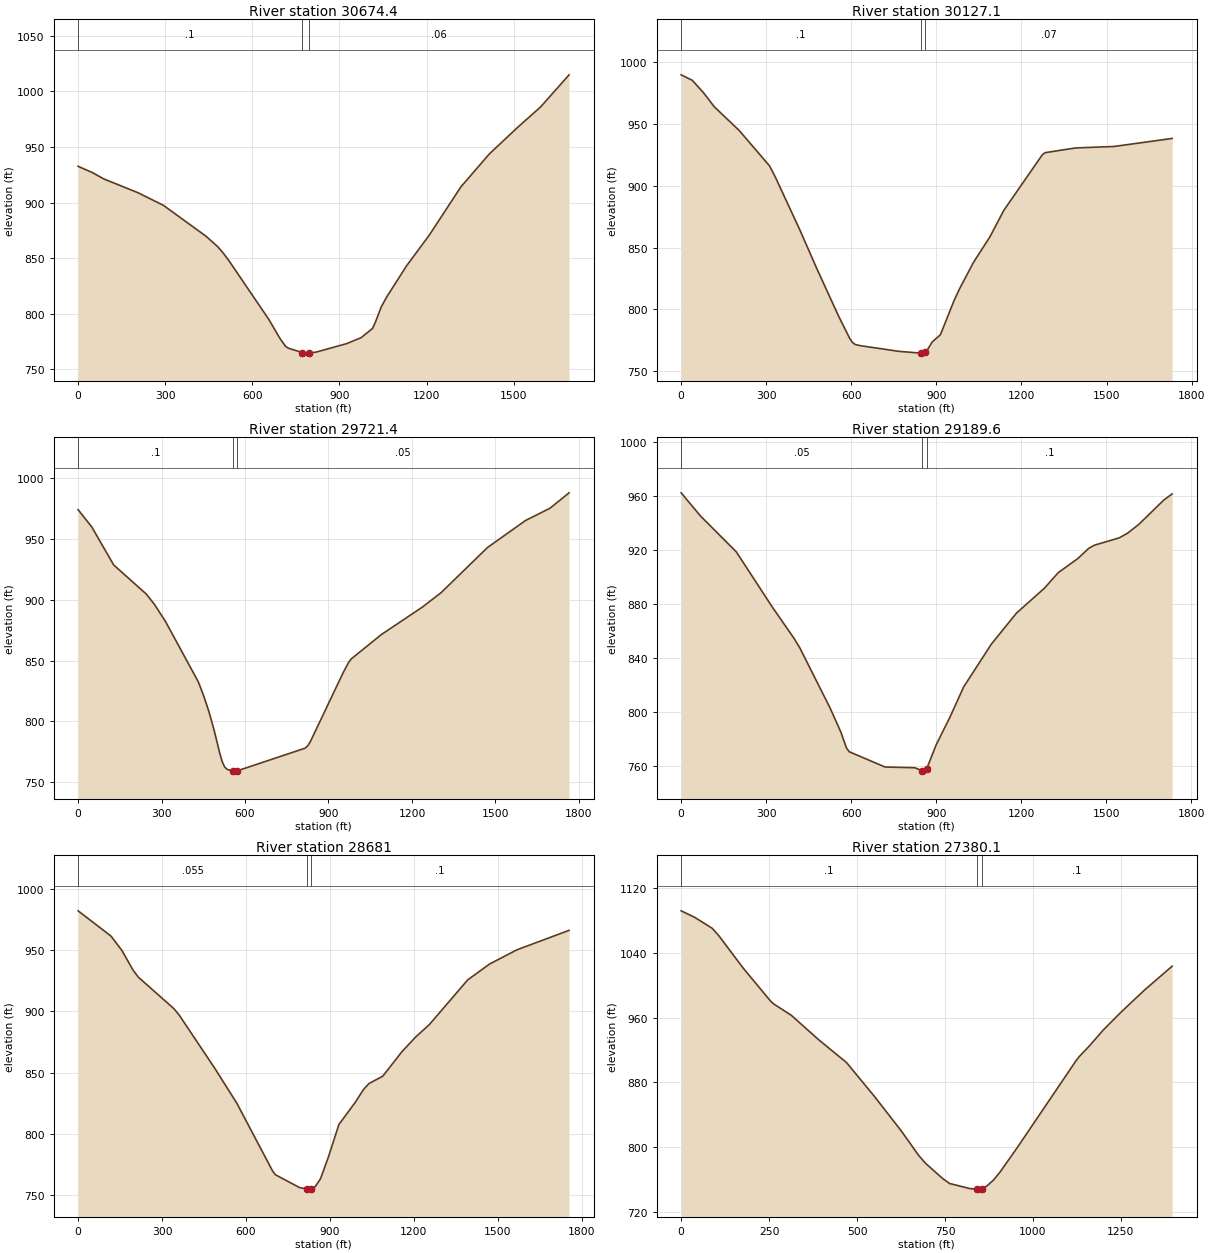
Type RM Length L Ch R = 1 ,30674.4 ,537.2,547.3,554.5
XS GIS Cut Line= 4
     1532491.022      199080.843     1532209.772       199685.01
     1532209.772      199924.593     1532423.314      200679.801
#Sta/Elev= 30
       0  932.61      49  927.01    88.2   921.3   205.8   908.9     294  897.48
     441  869.61   480.2  860.45   499.8  854.56   519.4  847.74   656.6  794.96
   695.2   777.7   714.3  770.68   723.9     769   771.8  765.06     791  764.52
   794.9  764.53   819.8  765.44   925.6  773.12   974.7  778.44  1013.9  786.67
  1023.7  792.25  1043.4  805.78    1063  815.15  1131.6  843.19  1210.1  870.92
    1318  914.02  1416.1   943.7  1514.2  967.77  1592.7  985.98  1690.8 1014.91
#Mann= 3 , 0 , 0
       0      .1       0   771.8    .045       0   794.9     .06       0
Bank Sta=771.8,794.9
XS Rating Curve= 0 ,0
Exp/Cntr=0.3,0.1

Type RM Length L Ch R = 1 ,30127.1 ,410,405.7,401.3
XS GIS Cut Line= 4
     1531605.605      199018.343     1531787.897      199695.426
      1531683.73       199935.01     1532037.897      200617.301
#Sta/Elev= 30
       0  989.82      39  985.41    77.9  975.59   116.9  963.94   204.5  944.79
   311.6  916.12   331.1  907.52   418.8  864.11   477.2   833.5   555.1  794.47
   594.1  776.54   603.8   773.2   613.5  771.51     633  770.49   768.9  765.91
   845.9   764.5   860.9  765.47   865.7  766.25     885  773.48   914.1  779.39
   962.4  807.13   981.9  816.71  1030.6  837.92  1088.9  858.73  1137.6  880.04
  1273.8   925.2  1283.6  926.81  1390.6  930.62  1526.8  931.82  1731.2  938.32
#Mann= 3 , 0 , 0
       0      .1       0   845.9    .045       0   860.9     .07       0
Bank Sta=845.9,860.9
XS Rating Curve= 0 ,0
Exp/Cntr=0.3,0.1

Type RM Length L Ch R = 1 ,29721.4 ,540.3,531.8,523.3
XS GIS Cut Line= 4
     1531480.605       199028.76     1531444.147      199440.218
     1531386.855      199690.218     1531267.064       200778.76
#Sta/Elev= 30
       0  973.84    49.2  959.64   127.9  928.47   245.9  904.39   275.4  895.78
   314.7  881.83   432.1  832.49   451.1  821.23   470.1  808.18   489.1  792.72
   508.1  774.96   517.6  767.22   527.1  762.47   536.6  760.55   556.6  759.33
   565.1   759.2   571.6  759.41   816.2  778.06     826   780.1   835.8  783.89
   953.1  840.17   972.7  848.57   982.4  851.42    1090   871.3  1236.7  893.74
  1305.1  905.78  1471.3  942.73  1608.2  964.94  1696.2  975.01  1764.7  987.66
#Mann= 3 , 0 , 0
       0      .1       0   556.6    .045       0   571.6     .05       0
Bank Sta=556.6,571.6
XS Rating Curve= 0 ,0
Exp/Cntr=0.3,0.1

Type RM Length L Ch R = 1 ,29189.6 ,536.7,508.6,479.2
XS GIS Cut Line= 4
     1530501.439      198763.135     1530866.022      199405.496
       1530893.8      199592.996     1531109.078      200367.301
#Sta/Elev= 30
       0   962.2      68  945.12   194.4  918.59   320.7     878   398.5   854.5
   417.9  847.84   524.8  803.33   563.7  785.13   583.1   773.6   592.8  770.78
   719.2  759.49   823.9  758.96   850.4  756.76   861.8  756.45   865.4  757.85
   899.7  775.99   947.8  796.23   996.8  818.84  1094.8  850.53    1183  873.33
    1281  891.63    1330  903.17  1398.6  913.52  1437.8  921.19  1457.4  923.47
  1545.6  928.93    1575  932.42  1614.2  938.86  1702.4  956.86  1731.8   961.4
#Mann= 3 , 0 , 0
       0     .05       0   850.4    .045       0   865.4      .1       0
Bank Sta=850.4,865.4
XS Rating Curve= 0 ,0
Exp/Cntr=0.3,0.1

Type RM Length L Ch R = 1 ,28681   ,1294.3,1300.9,1307.5
XS GIS Cut Line= 4
     1529952.828      199592.996     1530640.328       199849.94
     1530834.772      199888.135       1531081.3      200672.857
#Sta/Elev= 30
       0  981.82   117.4  961.28   156.6  949.53   195.7  933.79   215.3  927.75
   342.5  902.09   362.1  896.62   489.3  853.21   567.6   824.9   694.8  769.92
   704.6   766.8   790.6  756.37   817.8  755.01   818.9     755   832.8  755.21
   847.2  756.95     866   763.3   894.4  781.07   932.1  807.68   990.9  825.87
  1020.2  836.27  1039.8  841.08  1088.8  847.04  1157.3  867.01  1206.3  878.95
  1255.2  889.08  1392.3  925.52  1470.7  938.48  1568.6  950.07  1754.6  965.91
#Mann= 3 , 0 , 0
       0    .055       0   817.8    .045       0   832.8      .1       0
Bank Sta=817.8,832.8
XS Rating Curve= 0 ,0
Exp/Cntr=0.3,0.1

Type RM Length L Ch R = 1 ,27380.1 ,1471.9,1489.4,1506.5
XS GIS Cut Line= 4
     1529551.786      200730.843     1530234.078      201001.676
     1530437.203      201111.051     1530827.828      201293.343
#Sta/Elev= 30
       0 1091.65    39.2 1083.43    88.1 1070.14   107.7 1060.64   176.2 1021.08
   254.5  980.16   264.3  976.45   313.2  962.78   391.5  932.46   469.8  904.65
   548.1  863.51   626.4  819.84   675.4  789.88   694.9  780.21   743.7  761.38
   762.9  755.37   820.6  749.09   839.8   748.4     856  748.82   868.6  752.08
   887.9  759.57   907.1  769.78   955.2  799.43  1121.5  906.08  1131.3  911.67
  1160.7   925.1  1199.9  944.61  1248.9  966.01  1317.5  994.04  1395.8 1023.36
#Mann= 3 , 0 , 0
       0      .1       0   839.8    .045       0     856      .1       0
Bank Sta=839.8,856
XS Rating Curve= 0 ,0
Exp/Cntr=0.3,0.1

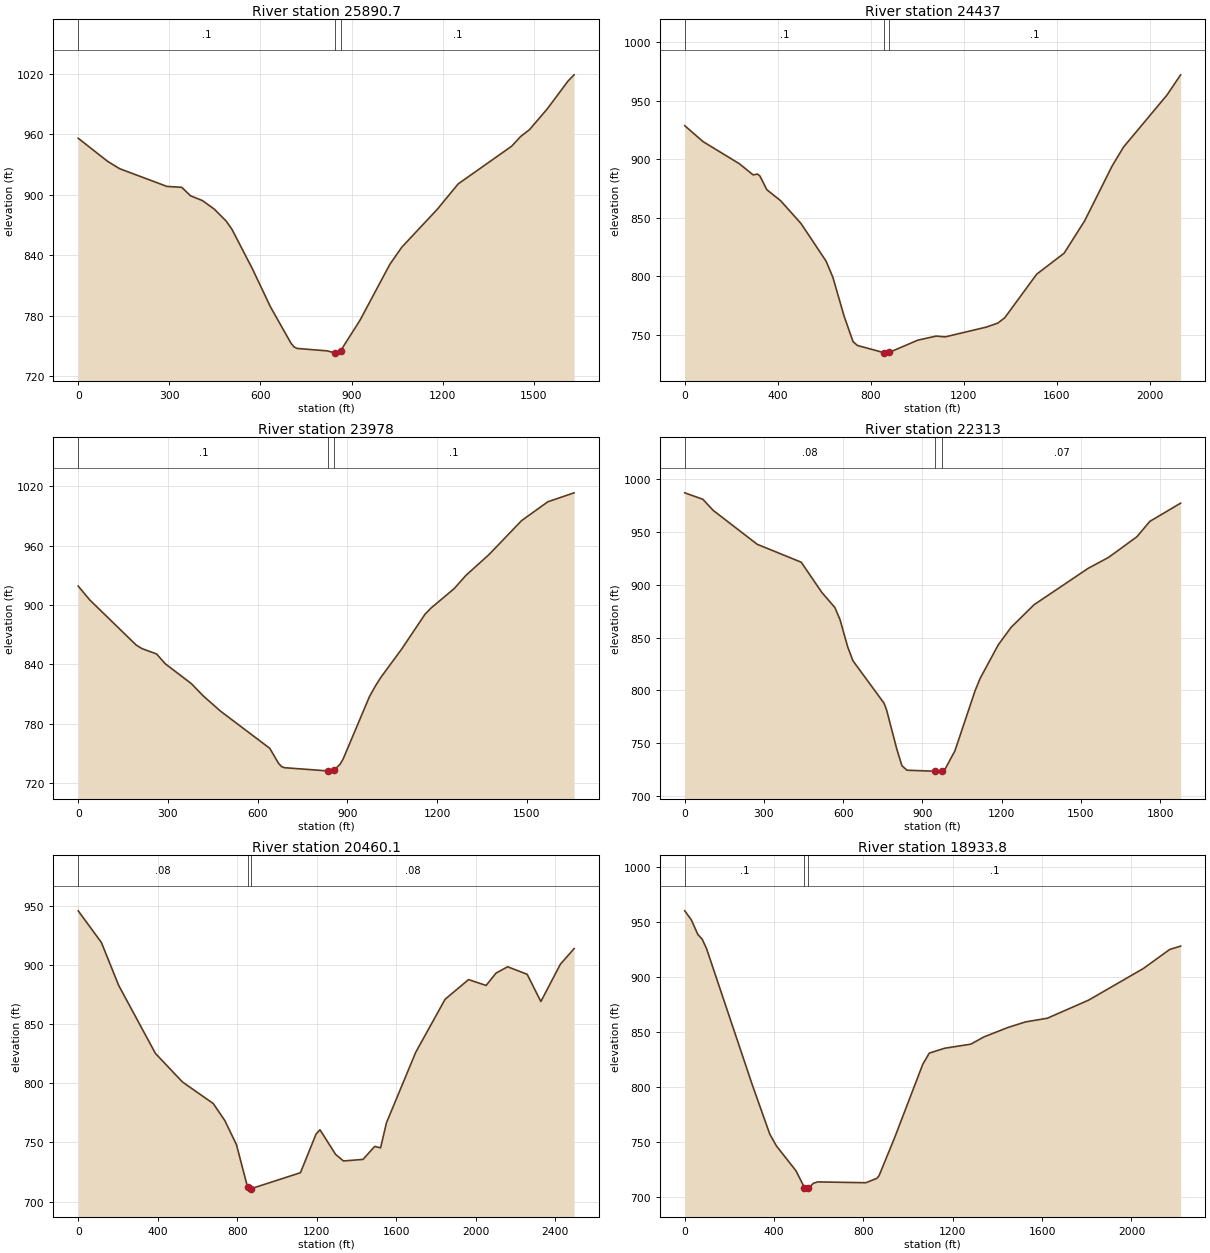
Type RM Length L Ch R = 1 ,25890.7 ,1471.6,1453.7,1434.8
XS GIS Cut Line= 4
     1528838.244      201454.801     1529333.036      201923.551
     1529437.203      202251.676     1529937.203      202595.426
#Sta/Elev= 30
       0  956.24    97.4   933.2   136.3  926.02   292.1  908.42   340.8  907.52
     370  899.08     409  894.36   447.9   885.9   486.8  874.13   506.3  865.78
   574.5     826   632.9  788.86   701.2   752.4   711.1  748.97   720.9  747.54
   819.3  745.12   845.2  743.18   848.8  742.88  864.29745.4212   927.5   775.4
  1025.8  830.94    1065  847.94  1182.4  885.78  1250.9   910.9  1427.1  948.35
  1456.4  957.92  1485.8   964.8  1544.5  985.47    1613  1013.2  1632.6 1019.22
#Mann= 3 , 0 , 0
       0      .1       0   845.2    .045       0  864.29      .1       0
Bank Sta=845.2,864.29
XS Rating Curve= 0 ,0
Exp/Cntr=0.3,0.1

Type RM Length L Ch R = 1 ,24437   ,433.5,459,484.4
XS GIS Cut Line= 4
     1528452.828      202605.843     1528999.703      202970.426
     1529249.703      203090.218     1530426.786      203319.385
#Sta/Elev= 30
       0  928.58    78.5  915.04   235.4  896.03   294.3  886.56   313.9  887.24
   323.7  885.55   353.2  873.89     412  864.62   500.3  845.03   608.2   812.9
   637.6  798.97   685.9  765.81   724.2  744.12   743.3  740.84   859.5  734.57
   867.6   734.3  879.43734.8933  1003.3  745.39  1081.9  748.85  1121.2   748.2
  1298.2  756.55  1347.3  759.98  1376.8  764.46  1514.4  801.74  1632.4  819.65
  1720.8  847.33  1838.8  894.09  1887.9   910.3  2074.7  954.69  2133.7  972.04
#Mann= 3 , 0 , 0
       0      .1       0   859.5    .045       0  879.43      .1       0
Bank Sta=859.5,879.43
XS Rating Curve= 0 ,0
Exp/Cntr=0.3,0.1

Type RM Length L Ch R = 1 ,23978   ,1678.3,1664.9,1649.3
XS GIS Cut Line= 4
     1528301.786      202626.676     1528796.578      203032.926
     1528796.578       203366.26     1529036.161      204006.885
#Sta/Elev= 30
       0  919.08    38.8  904.99     194  859.42   213.4  855.84   261.9  850.48
     291  840.54   378.3  820.47   417.1  808.33   475.3  792.76   640.2  755.12
   669.6  739.94   679.4  736.71   689.2  735.52   836.3  732.21   846.1  732.05
   855.9  733.25   875.5  739.08   885.3  744.16   973.5  807.35   993.1  817.95
  1012.6  827.22    1081  855.33  1159.2   890.6  1178.7  896.71  1256.9  916.55
    1296  929.87  1374.1  951.21  1481.6  985.13  1569.6 1004.25  1657.5 1013.31
#Mann= 3 , 0 , 0
       0      .1       0   836.3    .045       0   855.9      .1       0
Bank Sta=836.3,855.9
XS Rating Curve= 0 ,0
Exp/Cntr=0.3,0.1

Type RM Length L Ch R = 1 ,22313   ,1840.2,1852.9,1866.8
XS GIS Cut Line= 4
     1527395.536      203126.676     1527885.119      203751.676
     1528098.661      203996.468     1528655.953      204512.093
#Sta/Elev= 30
       0  987.21    68.6   981.1   107.8  970.56   274.4  938.41   441.1  921.43
   519.5  892.68   568.5   878.5   588.1  866.96   617.5  840.85   637.1  827.94
   754.7  787.76   764.5  781.31   803.5  743.85   822.6   728.4   841.7  724.17
   937.2   723.3   946.8   723.3   975.4   723.4     985  724.76  1023.2  742.53
  1099.7  799.62  1118.8  811.26  1186.9  842.88  1235.6  859.55  1323.2  881.14
  1527.6  915.56  1605.5  926.04  1712.5  945.57  1761.2  960.09    1878   977.4
#Mann= 3 , 0 , 0
       0     .08       0   946.8    .045       0   975.4     .07       0
Bank Sta=946.8,975.4
XS Rating Curve= 0 ,0
Exp/Cntr=0.3,0.1

Type RM Length L Ch R = 1 ,20460.1 ,1532.3,1526.3,1517.3
XS GIS Cut Line= 4
     1526650.744      203782.926     1526744.494      204475.635
     1526754.911      204756.885     1526921.578      206262.093
#Sta/Elev= 30
       0  945.64   116.5  918.96   203.9  882.55   388.4  825.22   524.3  801.09
   679.6  782.82   737.8  768.42   796.1  748.14   852.1  712.23     864  710.54
   867.1  710.77  1118.1   724.4  1196.8   757.1  1216.5  760.67  1295.2  739.84
  1334.5  734.34  1432.8  735.64  1491.8  746.62  1521.3  745.43  1550.8  766.56
  1698.3  826.19  1845.8   870.9  1963.8  887.54  2052.4  882.61  2101.5  892.94
  2160.5   898.4  2258.9     892  2327.7  869.01    2426  900.56  2494.9  913.72
#Mann= 3 , 0 , 0
       0     .08       0   852.1    .045       0   867.1     .08       0
Bank Sta=852.1,867.1
XS Rating Curve= 0 ,0
Exp/Cntr=0.3,0.1

Type RM Length L Ch R = 1 ,18933.8 ,2442.3,2456.9,2467.2
XS GIS Cut Line= 4
     1525306.994      203569.385     1525515.328      203933.968
     1525614.286      204189.176     1526208.036      205595.426
#Sta/Elev= 30
       0  960.25    29.3  952.15    58.6  938.79    78.1  934.46    97.6  925.94
   302.7  801.81   380.8  757.15   410.1  746.52   498.1  723.78  535.81708.5587
     547   707.1     552  707.83   576.3  712.45   595.9  713.67     811  712.92
     860  716.91   869.8  719.25   938.3  753.19  1065.5  820.54  1094.8  830.82
  1163.3  835.24  1280.7  838.97  1339.4  845.54  1447.1  854.15  1525.4  859.18
  1623.2  862.54  1809.1   879.1  2053.8  907.85  2171.2   925.1  2220.1  928.16
#Mann= 3 , 0 , 0
       0      .1       0  535.81    .045       0     552      .1       0
Bank Sta=535.81,552
XS Rating Curve= 0 ,0
Exp/Cntr=0.3,0.1

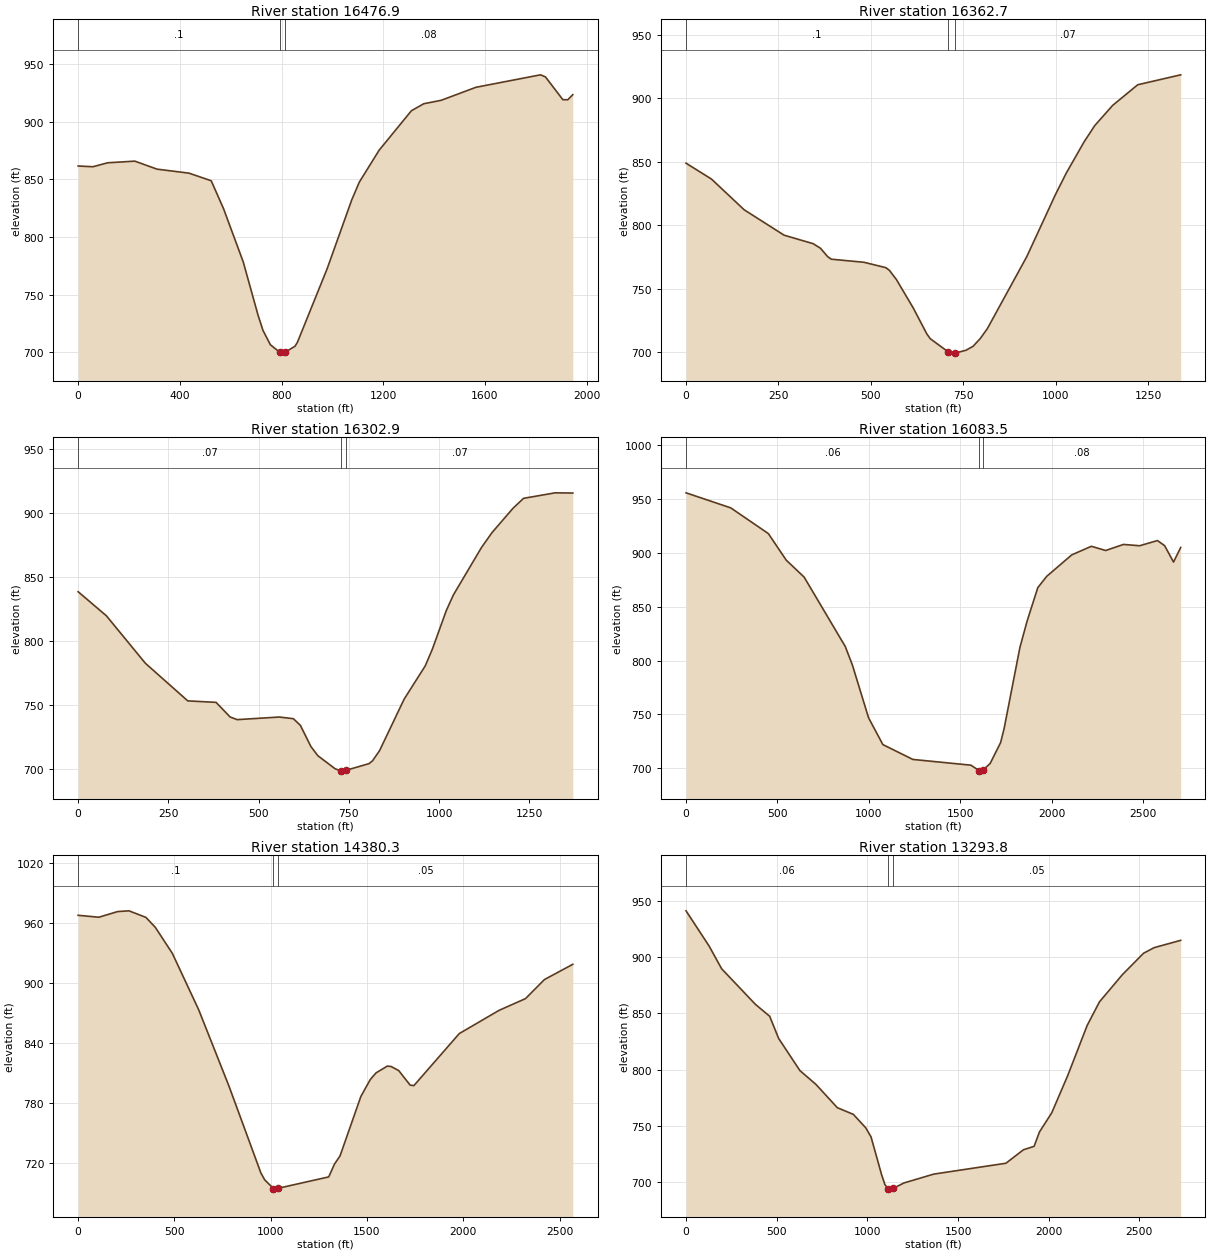
Type RM Length L Ch R = 1 ,16476.9 ,118.7,114.2,109.8
XS GIS Cut Line= 4
     1523957.978      204226.778     1523822.619       204772.51
     1523744.494       205241.26     1523806.994       206147.51
#Sta/Elev= 30
       0  861.49    58.2  860.87   116.3  864.29     223  865.71   310.2  858.78
   436.2   855.3   523.5  848.71     572   824.5   649.6  778.29   707.7  732.23
   727.1  719.04   756.2   706.6  792.21700.1996   804.7  699.31   812.5  699.86
   853.2  705.29   862.9  708.85   979.3  772.32  1076.6  832.29  1105.9  847.44
    1184  875.16    1311  909.41  1359.8  915.48  1428.2  918.45  1564.9  929.72
  1818.9  940.53  1838.4  938.74  1906.8  918.99  1926.4  918.94  1945.9  923.33
#Mann= 3 , 0 , 0
       0      .1       0  792.21    .045       0   812.5     .08       0
Bank Sta=792.21,812.5
XS Rating Curve= 0 ,0
Exp/Cntr=0.3,0.1

Type RM Length L Ch R = 1 ,16362.7 ,58.8,59.8,60.4
XS GIS Cut Line= 5
     1523647.619      204260.531     1523642.411      204820.426
     1523673.661       204935.01     1523676.265      205013.135
     1523668.453      205593.864
#Sta/Elev= 30
       0  848.76    68.8  836.25   157.2  812.07   265.2  792.08   343.8  785.39
   363.5   781.8   383.1  775.15   392.9  773.18   481.3  770.75   540.3  766.52
   550.1  764.36   569.1  757.07   614.7  734.64   651.3  714.29   660.4  710.61
     708  700.43   727.5  699.25   727.7  699.26   756.9   701.5   776.2  704.63
   795.6  710.71   814.9  718.58   921.4  775.18   998.8  823.95  1027.9  840.79
  1076.3  865.49  1105.3  878.37  1153.7  894.26  1221.5  910.49  1337.6   918.3
#Mann= 3 , 0 , 0
       0      .1       0     708    .045       0   727.7     .07       0
Bank Sta=708,727.7
XS Rating Curve= 0 ,0
Exp/Cntr=0.3,0.1

Type RM Length L Ch R = 1 ,16302.9 ,223.5,219.4,214.8
XS GIS Cut Line= 5
     1523611.161      204231.885     1523600.744      204682.406
     1523616.369      204924.593     1523616.369      205007.926
     1523624.182      205601.676
#Sta/Elev= 30
       0  838.75    78.4  819.91   186.1  782.94   303.7  753.53   382.1  752.37
   421.2  740.92   440.8  738.89   557.4  740.92   596.3  739.62   615.7  734.45
   644.8  717.94   664.2  710.72   711.8  700.57   727.2  698.87   730.4  698.69
   742.2  699.34   805.9  704.53   815.6  706.75   835.1  714.64   903.2  754.87
   961.6   780.8   981.1  793.67    1020  823.99  1039.5  836.14  1117.4   873.2
  1146.6  884.86    1205  903.93  1234.2  911.65  1321.8  915.94  1370.5  915.77
#Mann= 3 , 0 , 0
       0     .07       0   727.2    .045       0   742.2     .07       0
Bank Sta=727.2,742.2
XS Rating Curve= 0 ,0
Exp/Cntr=0.3,0.1

Type RM Length L Ch R = 1 ,16083.5 ,1716,1703.2,1689.3
XS GIS Cut Line= 5
     1522405.953      203876.676     1523254.911       204585.01
     1523405.953       204928.76     1523473.661      205256.885
     1523629.911      206131.885
#Sta/Elev= 30
       0  955.57   244.6  941.61   450.1  917.78   547.9  893.13   645.8  877.42
   870.8  813.04     910  795.75     998  747.02  1076.3   722.1  1240.4  708.32
  1557.7     703    1603  697.97  1615.1  697.48  1624.7  698.62    1663  704.55
  1720.4  723.98  1739.6  737.08  1825.9  812.23    1865  836.52  1923.6  867.62
  1972.4  878.12  2109.2  898.02  2216.6  905.99  2294.8  902.08  2392.4  907.72
  2480.4  906.48    2578   911.3  2617.1   906.6  2665.9  891.36    2705  904.87
#Mann= 3 , 0 , 0
       0     .06       0    1603    .045       0  1624.7     .08       0
Bank Sta=1603,1624.7
XS Rating Curve= 0 ,0
Exp/Cntr=0.3,0.1

Type RM Length L Ch R = 1 ,14380.3 ,1084.5,1086.5,1087.2
XS GIS Cut Line= 4
     1521368.105      205352.545     1521949.703      205890.739
     1522305.605       206211.92     1523564.286       206524.42
#Sta/Elev= 30
       0   967.5   107.6  965.57   205.4  971.23   264.1  971.96   352.2  965.39
   401.1   955.4   489.1  929.54   626.1  873.16   782.6  797.32     949  710.28
   968.5  703.49 1014.35694.7653  1027.2  694.15    1037  694.92  1301.3  706.36
  1330.8  719.01  1360.2   727.4  1468.3  786.69  1517.4  803.65  1546.9  810.17
  1605.8  816.98  1625.5  816.53  1664.8   812.5  1723.8  798.03  1743.4  797.45
  1979.2  849.42  2185.5  872.57  2323.1  884.32  2421.3  903.32  2568.7  918.57
#Mann= 3 , 0 , 0
       0      .1       0 1014.35    .045       0    1037     .05       0
Bank Sta=1014.35,1037
XS Rating Curve= 0 ,0
Exp/Cntr=0.3,0.1

Type RM Length L Ch R = 1 ,13293.8 ,3069.3,3084,3085.9
XS GIS Cut Line= 5
     1521484.425      205878.586       1521531.3      206878.586
     1521724.008      207050.461       1522281.3       207180.67
     1523104.217      207534.836
#Sta/Elev= 30
       0  941.37   127.6  909.92   196.3  889.77   382.8  858.06   461.3   847.5
   510.4  827.82   628.1   799.1   716.5  786.83   834.2   766.1   922.6  760.16
   991.3  748.12  1020.2  740.06  1077.6  706.85  1096.7  697.64  1115.9   693.6
 1141.03694.1602  1201.9  699.11    1366  706.97  1763.7  716.63  1860.8  728.67
  1919.3  731.68  1948.5  744.39  2016.6  761.58  2104.3  794.56  2211.4  839.17
  2279.6  860.31  2406.2  884.56    2523  903.64  2581.4  908.59  2727.5   915.1
#Mann= 3 , 0 , 0
       0     .06       0  1115.9    .045       0 1141.03     .05       0
Bank Sta=1115.9,1141.03
XS Rating Curve= 0 ,0
Exp/Cntr=0.3,0.1