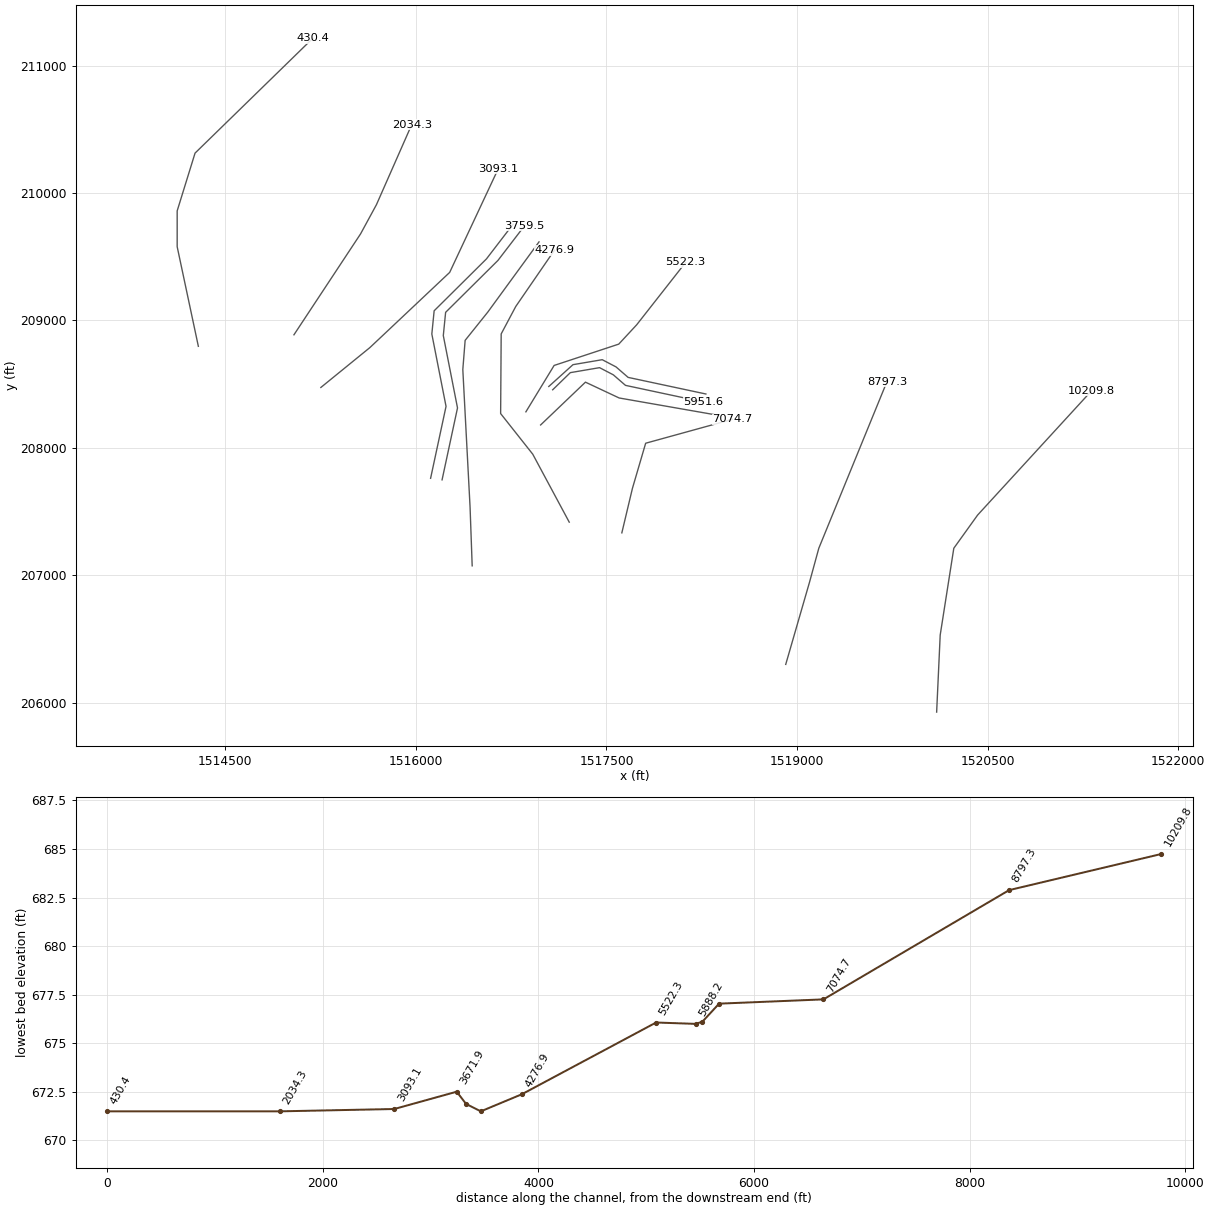
HEC-RAS study LTHRBRKCR.prj: LTHRBRKCR

--- LTHRBRKCR.g01 (geometry) --- (continued)

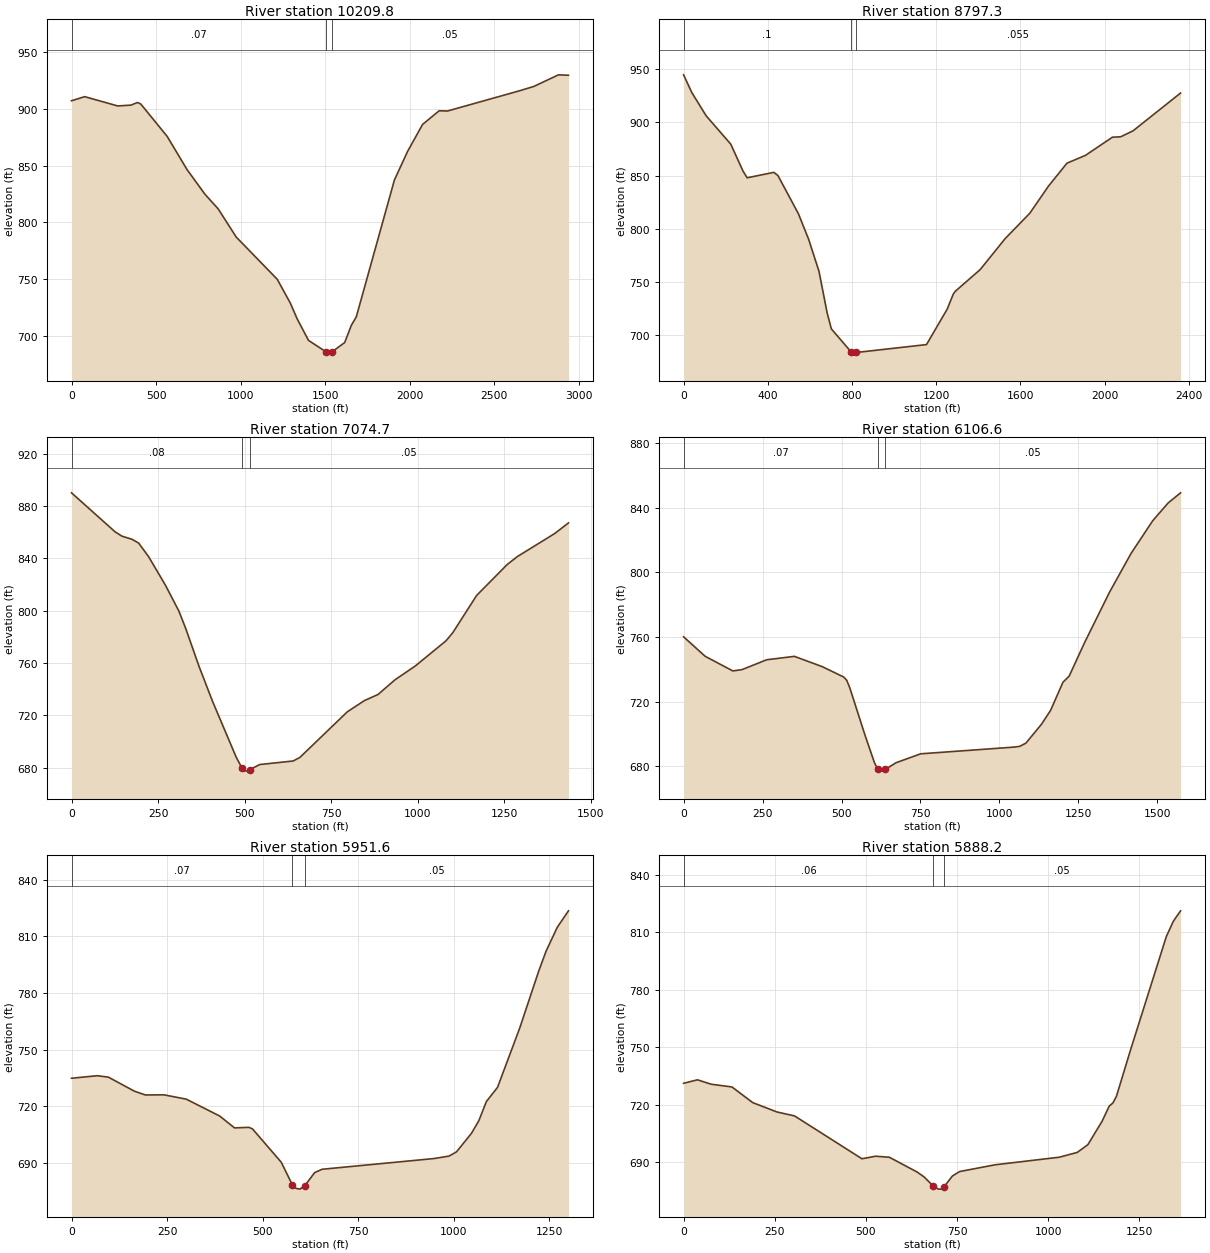
Type RM Length L Ch R = 1 ,10209.8 ,1407.6,1412.5,1415.7
XS GIS Cut Line= 5
     1520098.603      205927.299     1520126.586      206531.657
      1520233.73      207212.788      1520421.23      207473.204
     1521317.064      208447.163
#Sta/Elev= 30
       0  907.22    78.1  910.85   273.2  902.65   351.3  903.38   390.3   905.7
   409.8  904.33     566  875.75   682.7  846.66   789.5  824.73   867.2  811.93
     974  787.08  1216.8   749.8  1294.5  728.67  1333.4  715.26  1401.5  695.95
 1504.69685.9307  1518.2  684.74  1537.6  685.54  1615.4  694.08  1654.6  709.23
    1684   716.7  1909.5  837.42  1987.9  862.74  2076.1  886.38  2174.1  898.41
  2223.1  898.18  2644.6  915.83  2732.9   919.8  2879.9  930.09  2938.7  929.72
#Mann= 3 , 0 , 0
       0     .07       0 1504.69    .045       0  1537.6     .05       0
Bank Sta=1504.69,1537.6
XS Rating Curve= 0 ,0
Exp/Cntr=0.3,0.1

Type RM Length L Ch R = 1 ,8797.3  ,1722.7,1722.6,1720.7
XS GIS Cut Line= 4
     1518910.814      206301.329     1519098.314      206947.163
      1519171.23      207212.788     1519707.689      208520.079
#Sta/Elev= 30
       0  944.79      39  928.12   107.2  906.21   224.2  879.54   282.6  854.07
   302.1  847.89   428.8     853   448.3  849.96   545.8  813.92   594.5  789.77
   643.3  759.83   682.3  720.44     702  705.71  794.66684.2744   810.2  682.88
   820.1  683.49    1154  690.91  1252.2  724.23  1281.6  738.61  1291.4  741.18
  1409.2  761.53  1526.9  790.48  1644.7  814.52    1733  839.92  1821.3  861.63
  1909.6  869.04  2037.2  886.08  2076.4  886.47  2135.3  892.08    2361  927.66
#Mann= 3 , 0 , 0
       0      .1       0  794.66    .045       0   820.1    .055       0
Bank Sta=794.66,820.1
XS Rating Curve= 0 ,0
Exp/Cntr=0.3,0.1

Type RM Length L Ch R = 1 ,7074.7  ,1006.2,968.1,930.7
XS GIS Cut Line= 4
     1517620.883      207333.447     1517704.217      207682.406
     1517808.383      208036.572     1518490.675      208224.072
#Sta/Elev= 30
       0  890.16     126   860.3   145.4  857.03   174.5  854.65   193.9  851.73
     223  841.22   271.5  819.41   310.3  799.62   329.7  786.53   368.5  757.28
   407.4  730.64   475.4  688.11  492.46 679.525   504.5  677.26   514.2  678.24
   543.4  682.29   640.5  685.02   659.9   687.8   796.7  722.65   845.9   731.2
   885.2  735.86   934.3   747.1   993.3  757.75  1081.7  776.95  1101.4  783.19
  1170.2  811.65  1258.6  835.34  1288.1  841.43  1396.2  859.11  1435.5  867.16
#Mann= 3 , 0 , 0
       0     .08       0  492.46    .045       0   514.2     .05       0
Bank Sta=492.46,514.2
XS Rating Curve= 0 ,0
Exp/Cntr=0.3,0.1

Type RM Length L Ch R = 1 ,6106.6  ,161.6,154.9,147.4
XS GIS Cut Line= 4
     1516981.589      208179.801     1517334.425      208515.739
     1517599.645      208391.607       1518381.3      208255.322
#Sta/Elev= 30
       0  760.13    68.2  748.08   155.9  739.02   185.1  739.84   263.1  745.93
   350.8  748.03   438.5  741.71   506.7  735.27   516.5  733.23   526.2  728.58
     575  698.91   604.3  682.27   614.1  678.33   623.8  677.04  638.44678.1072
   672.6  682.23   750.7  687.75  1044.5  691.87  1064.1  692.36  1083.7  694.34
  1132.7  705.92    1162  714.63  1201.2  732.04  1220.8  735.82  1269.8  756.61
  1348.2  787.57  1416.7  811.68  1485.3  831.92  1534.3  842.94  1573.5  849.19
#Mann= 3 , 0 , 0
       0     .07       0   614.1    .045       0  638.44     .05       0
Bank Sta=614.1,638.44
XS Rating Curve= 0 ,0
Exp/Cntr=0.3,0.1

Type RM Length L Ch R = 1 ,5951.6  ,63.4,63.4,63.2
XS GIS Cut Line= 6
     1517076.612      208455.843     1517215.501      208590.392
     1517445.536      208629.454     1517554.043      208573.031
     1517649.529      208490.565     1518261.508      208360.357
#Sta/Elev= 30
       0  734.88    67.7  736.22    96.7  735.44   164.4  728.04   193.4  726.01
     242  726.08   300.3   723.8   387.8  714.86   426.7  708.56   464.3  708.86
   473.7  708.03     549  690.36   578.1  678.33   587.8  676.54   597.5  676.11
  610.25677.8121   636.4  684.86   655.8  686.63   948.9  692.32     988  693.61
  1007.6  695.85  1046.7  705.63  1066.2  712.38  1085.8   722.5  1115.1  730.04
  1173.8  761.82  1222.6  791.49  1242.2  802.22  1271.5  814.89  1300.8   823.6
#Mann= 3 , 0 , 0
       0     .07       0   578.1    .045       0  610.25     .05       0
Bank Sta=578.1,610.25
XS Rating Curve= 0 ,0
Exp/Cntr=0.3,0.1

Type RM Length L Ch R = 1 ,5888.2  ,330.8,365.9,400.3
XS GIS Cut Line= 6
     1517045.999      208481.812     1517236.335      208652.892
     1517466.369      208691.954     1517574.876      208635.531
     1517670.362      208553.065     1518282.342      208422.857
#Sta/Elev= 30
       0  731.19    37.9  733.02    75.8  730.72   132.7  729.29   189.6  721.13
   255.9  716.26   304.5  714.18   489.2  691.84   526.9  693.17   564.5  692.62
   640.7  684.92   660.1  682.32  684.81 677.619   698.9     676   708.6     676
  714.45677.2122   737.7  682.88   757.3  685.18     855   688.7    1031  692.65
  1079.9  695.15  1109.2  699.19  1148.3  711.48  1167.9  719.37  1177.6  720.89
  1187.4  724.38  1226.5  748.81  1324.3  807.73  1343.8  815.78  1363.4  821.16
#Mann= 3 , 0 , 0
       0     .06       0  684.81    .045       0  714.45     .05       0
Bank Sta=684.81,714.45
XS Rating Curve= 0 ,0
Exp/Cntr=0.3,0.1

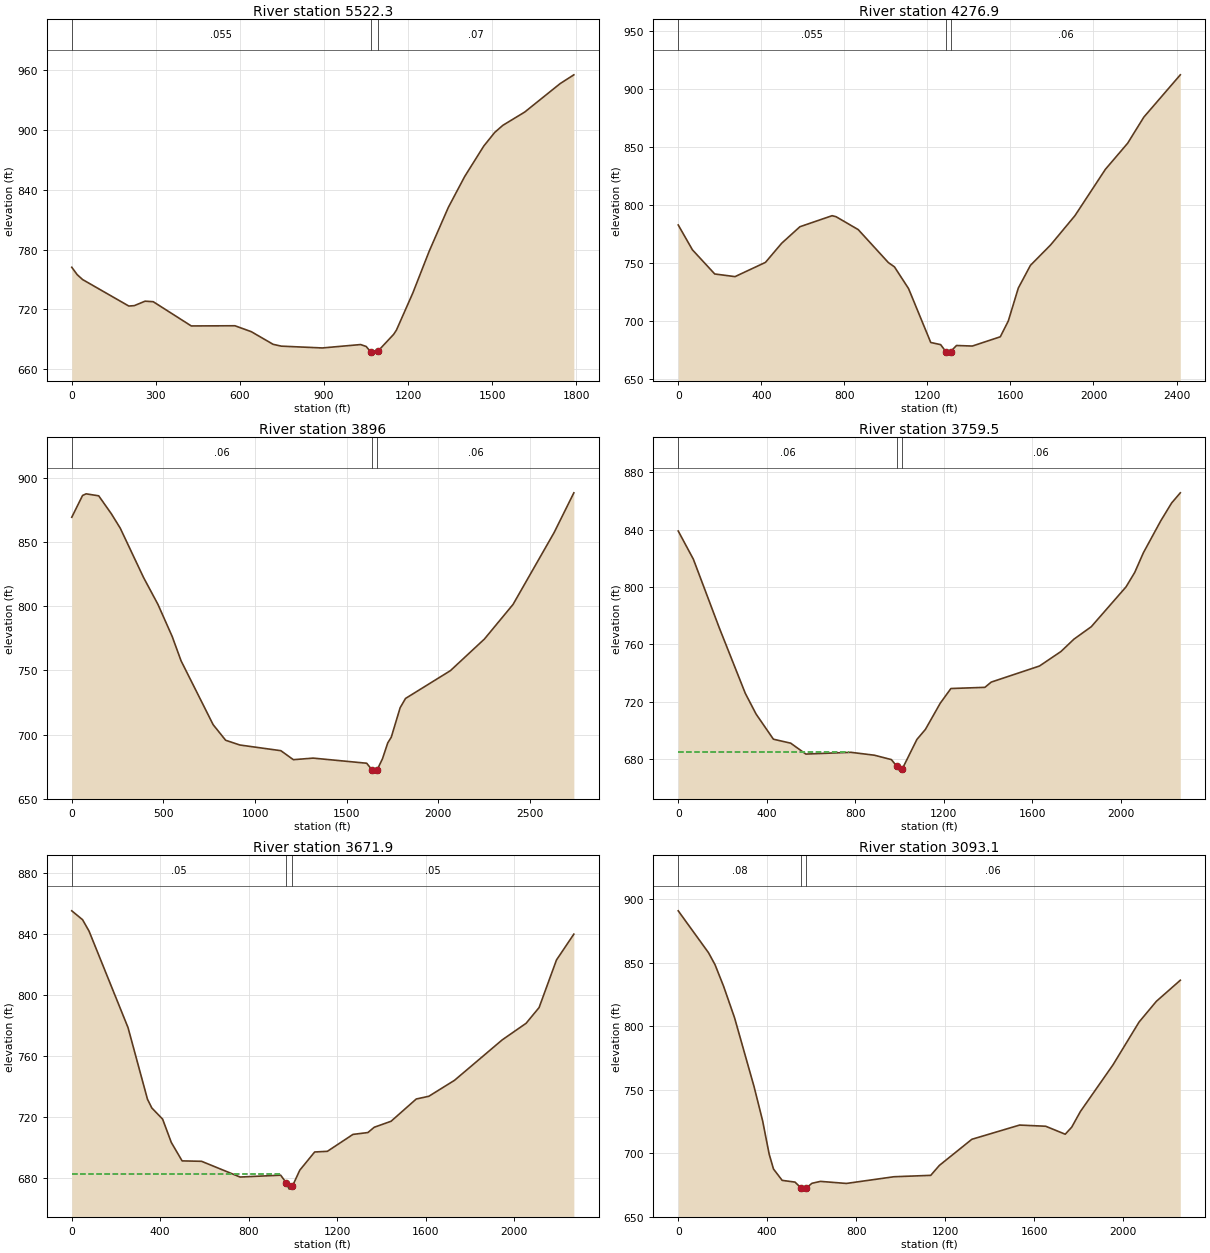
Type RM Length L Ch R = 1 ,5522.3  ,1228.4,1245.4,1258.8
XS GIS Cut Line= 5
     1516865.704      208282.883     1517087.897      208646.815
     1517596.607      208814.133     1517737.232      208965.175
     1518122.648      209454.758
#Sta/Elev= 30
       0  762.18    19.4  754.76    38.8  749.83   203.5   723.3   222.9  723.68
   261.6  728.17   290.7  727.64   426.4  703.33   582.2  703.52   640.6  697.58
   718.5  684.89   747.7  683.07   893.8  681.26  1030.7  684.67  1050.4  682.74
  1067.4677.0257  1079.8  676.07 1093.65678.4279  1148.6  694.94  1158.5  699.23
    1217  736.46  1275.4  778.35  1343.5  822.18    1402  853.25  1470.1  883.78
    1509   897.4  1538.2  904.56  1616.1  917.85  1742.7  946.43  1791.4  955.19
#Mann= 3 , 0 , 0
       0    .055       0  1067.4    .045       0 1093.65     .07       0
Bank Sta=1067.4,1093.65
XS Rating Curve= 0 ,0
Exp/Cntr=0.3,0.1

Type RM Length L Ch R = 1 ,4276.9  ,381.4,380.9,380.4
XS GIS Cut Line= 6
      1517206.85      207417.432     1516919.634      207950.685
      1516666.89      208269.211      1516671.23      208894.211
     1516785.843      209109.272      1517090.53      209551.112
#Sta/Elev= 30
       0  782.88    68.4  761.45   175.8  740.63   273.5  738.35   420.1  750.63
   498.2  767.13   586.1  781.37   741.2  790.89   760.6  789.98   867.1  778.87
  1012.3  750.43  1041.4  746.78  1109.4  728.03  1216.3  681.55  1263.9  679.71
    1290  673.43    1302  672.38  1311.6  673.66  1340.2  678.96  1416.4  678.48
  1551.2  686.46  1589.7  700.06  1637.9  728.43  1696.4  748.06  1793.9  765.73
  1910.9  790.94  2057.2  830.82  2164.6  853.36  2242.6  875.88  2418.3  912.36
#Mann= 3 , 0 , 0
       0    .055       0    1290    .045       0  1311.6     .06       0
Bank Sta=1290,1311.6
XS Rating Curve= 0 ,0
Exp/Cntr=0.3,0.1

Type RM Length L Ch R = 1 ,3896    ,130.8,136.5,142.2
XS GIS Cut Line= 6
     1516442.961       207074.55     1516426.387      207534.444
     1516369.281      208614.459      1516387.51      208843.625
     1516565.616       209065.16     1516969.002      209616.216
#Sta/Elev= 30
       0  869.29    58.8  886.26    78.3  887.55   146.9     886   215.4  872.12
   264.4  860.82   391.6  822.34   469.9  801.46   547.6  776.47   596.2  757.46
   771.1  707.72   839.2  695.57   916.9  691.85  1140.4  687.43    1209  680.42
  1316.6  681.64  1608.8  677.65  1637.5  672.52  1656.7   671.5  1666.2  672.59
    1695  681.16  1723.7  693.53  1742.9  697.94  1791.2  720.88  1820.6  728.12
  2065.6  749.79    2251  774.41  2407.1  801.37  2631.5  857.46  2738.8  888.33
#Mann= 3 , 0 , 0
       0     .06       0  1637.5    .045       0  1666.2     .06       0
Bank Sta=1637.5,1666.2
XS Rating Curve= 0 ,0
Exp/Cntr=0.3,0.1

Type RM Length L Ch R = 1 ,3759.5  ,87.7,87.6,87.5
XS GIS Cut Line= 6
     1516205.953      207749.246      1516327.48      208313.482
     1516215.675       208881.19     1516233.904      209063.482
     1516645.732      209470.702     1516855.287      209742.953
#Sta/Elev= 30
       0  838.94    68.5  819.32   185.9  771.47   303.3     726   352.2  711.54
   430.4  694.09   508.7  691.32   577.2  683.75   780.6  684.97   887.2  682.95
     964   679.9   988.5675.1771  1002.4  671.88    1012  673.06  1079.2   693.9
  1117.5  700.86  1184.8  719.12    1233  729.36  1386.7  730.17  1415.3  733.82
  1633.7  745.03  1730.6   755.1  1789.4   763.7  1867.9  772.38    2025  800.09
  2064.2  810.11  2103.5  823.84    2182  846.04  2231.1  858.45  2270.4  865.52
#Mann= 3 , 0 , 0
       0     .06       0   988.5    .045       0    1012     .06       0
#XS Ineff= 2 , 0
          771.31  685.32
Permanent Ineff=
       F       F
Bank Sta=988.5,1012
XS Rating Curve= 0 ,0
Exp/Cntr=0.3,0.1

Type RM Length L Ch R = 1 ,3671.9  ,600.6,578.8,556
XS GIS Cut Line= 6
     1516115.675      207761.399     1516237.203      208325.635
     1516125.397      208893.343     1516143.626      209075.635
     1516555.454      209482.855     1516765.009      209755.105
#Sta/Elev= 30
       0  855.43    48.9  849.59    78.3  842.05   254.4  778.69   342.4  731.58
     362  725.86   410.9   718.5     450  703.22   498.9  691.07   586.9   690.8
   761.2  680.46   944.9  681.67  969.51676.7121   983.2  672.51   997.7674.4496
  1031.2  684.98  1098.4  696.93  1155.9  697.36  1271.6  708.48  1339.1   709.7
  1367.7  713.17  1443.9  717.12  1557.8  731.75  1614.8  733.55  1730.6  744.01
  1946.4   770.6  2054.4   781.5  2113.3  791.86  2191.8   823.1  2270.4  840.11
#Mann= 3 , 0 , 0
       0     .05       0  969.51    .045       0   997.7     .05       0
#XS Ineff= 2 , 0
          946.27  682.31
Permanent Ineff=
       F       F
Bank Sta=969.51,997.7
XS Rating Curve= 0 ,0
Exp/Cntr=0.3,0.1

Type RM Length L Ch R = 1 ,3093.1  ,1051.2,1058.8,1066.3
XS GIS Cut Line= 5
      1515251.96      208474.072     1515637.376      208786.572
     1515748.487      208890.739     1516265.849       209376.85
     1516647.793       210189.35
#Sta/Elev= 30
       0  890.94   136.2   857.9   165.4  848.48   204.3  831.27     253  806.72
   340.5  752.55   379.4  725.32   408.6  699.22   428.1  687.46     467  678.53
   524.7  677.16   553.3  672.34   562.8  671.62  575.34672.4857   600.9  676.22
     639  677.72   755.5   676.1   969.4  681.38  1134.7  682.48  1173.6  690.33
  1319.5   710.9    1534   722.1  1651.2  721.18    1739  714.89  1768.3  720.48
  1807.3  732.81  1953.7  769.57  2070.8  803.28  2148.8  819.66  2256.2  836.24
#Mann= 3 , 0 , 0
       0     .08       0   553.3    .045       0  575.34     .06       0
Bank Sta=553.3,575.34
XS Rating Curve= 0 ,0
Exp/Cntr=0.3,0.1

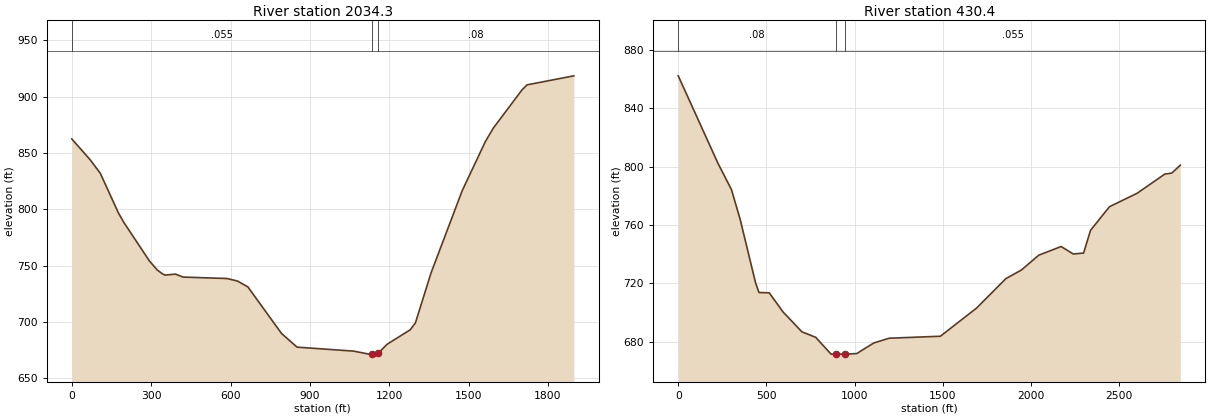
Type RM Length L Ch R = 1 ,2034.3  ,1590.8,1603.9,1613.9
XS GIS Cut Line= 4
     1515040.154      208887.267      1515564.46      209678.933
      1515689.46        209908.1     1515967.237      210536.572
#Sta/Elev= 30
       0  862.41    68.5  844.21   107.7     832   176.2  796.83   195.8  788.72
   293.7  754.09     323  746.18   342.6  742.76   352.4   741.6   391.6  742.48
   420.9  739.86   587.4  738.56   626.5  736.33   665.7  731.12   792.9  689.81
   851.6   677.7  1065.6  674.16  1123.6   671.5  1133.2   671.5  1157.9  672.11
  1191.2  680.14  1279.3   693.1  1298.9  699.22  1357.8  743.42  1475.6  816.42
    1564  860.41  1593.4  872.02  1701.4  905.79    1721  910.37  1897.7  918.38
#Mann= 3 , 0 , 0
       0    .055       0  1133.2    .045       0  1157.9     .08       0
Bank Sta=1133.2,1157.9
XS Rating Curve= 0 ,0
Exp/Cntr=0.3,0.1

Type RM Length L Ch R = 1 ,430.4   ,426.9,430.4,432.5
XS GIS Cut Line= 5
     1514287.724      208796.989     1514121.057      209578.239
     1514121.057      209859.489     1514261.682      210312.614
     1515188.765      211213.656
#Sta/Elev= 30
       0  862.34   224.1  802.66     302  784.27   350.7  764.13   438.4  720.47
   457.9  713.76   516.3  713.52   594.2  700.44   701.4   686.8   779.4  683.05
   866.7   671.5   895.8   671.5   944.3   671.5  1012.2  671.88  1109.1  679.15
  1196.3  682.41  1486.8  683.77  1691.6  703.05  1858.1  723.28  1946.3  729.18
  2044.2  739.32  2171.6   745.3  2240.1  740.16  2298.9  740.82    2338  756.37
  2445.8   772.6  2602.5  781.81  2759.2  794.96  2798.4  795.64  2847.3  801.03
#Mann= 3 , 0 , 0
       0     .08       0   895.8    .045       0   944.3    .055       0
Bank Sta=895.8,944.3
XS Rating Curve= 0 ,0
Exp/Cntr=0.3,0.1

Chan Stop Cuts=-1
Use User Specified Reach Order=0
Composite Channel Slope=5